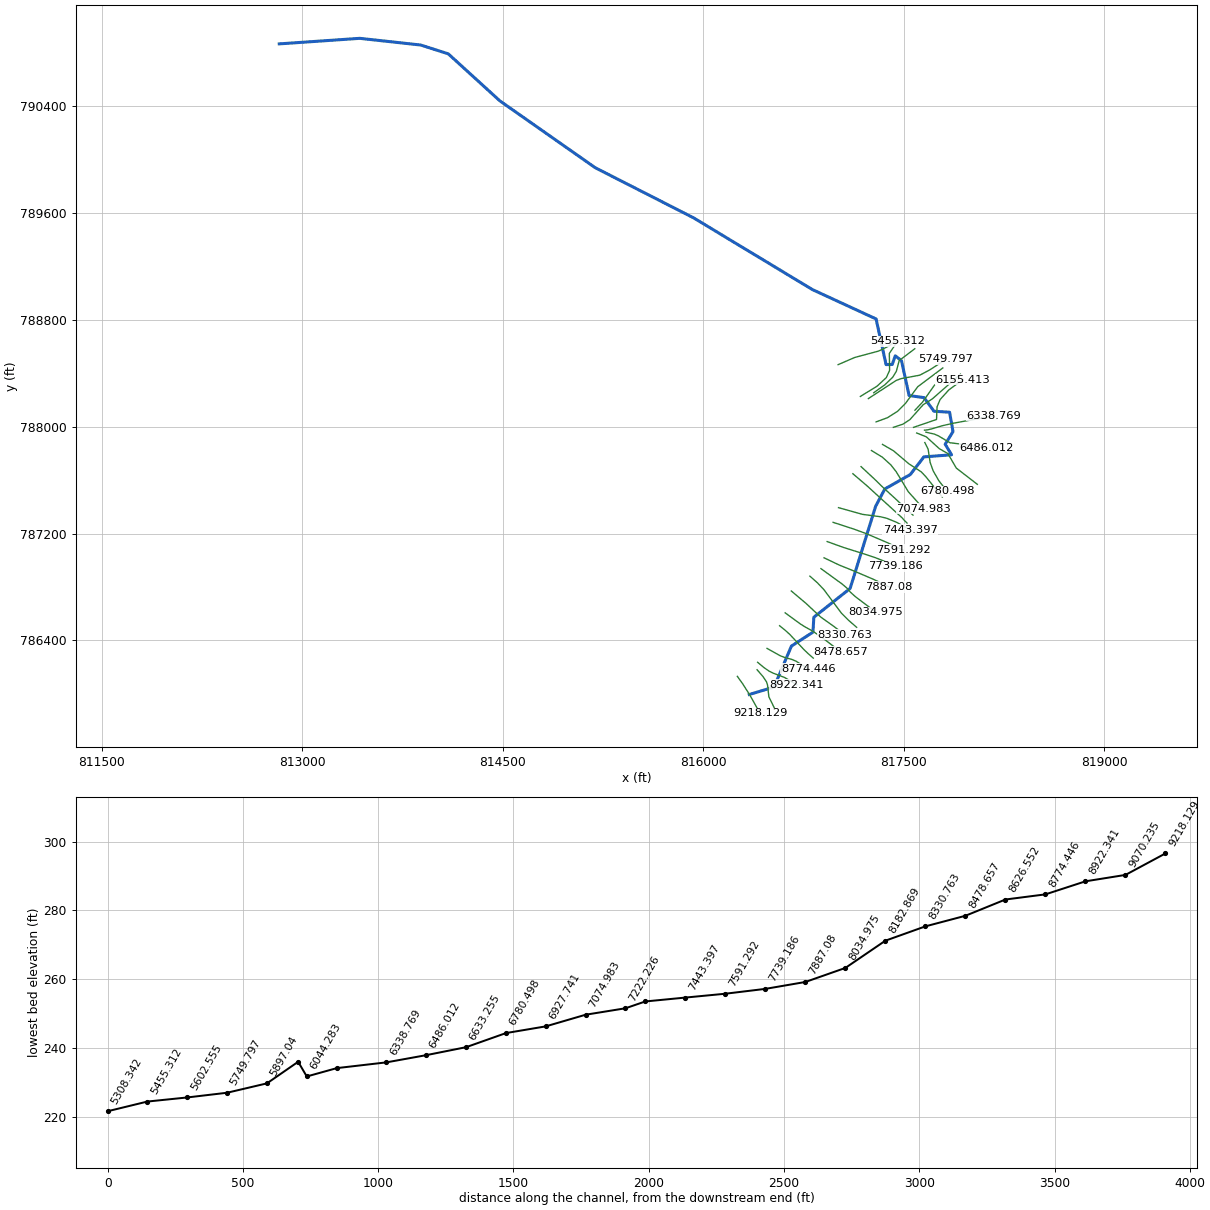
--- 17417_ras.prj (project) ---

Proj Title=17417
Current Plan=p01
Default Exp/Contr=0.3,0.1
English Units
Geom File=g01
Flow File=f01
Plan File=p01
Y Axis Title=Elevation
X Axis Title(PF)=Main Channel Distance
X Axis Title(XS)=Station
BEGIN DESCRIPTION:
RFD model 17417 exported to HEC-RAS
END DESCRIPTION:

--- 17417_ras.p01 (plan) ---

Plan Title=Plan 01
Program Version=4.10
Short Identifier=Plan 01
Geom File=g01
Flow File=f01
Subcritical Flow
Calc Critical at every XS
Secant Critical Depth

--- 17417_ras.f01 (steady flow) ---

Flow Title=Flow 01
Program Version=5.01
Number of Profiles= 6
Profile Names=10yr,25yr,50yr,100yr,100plus,500yr
River Rch & RM=17417,36,9218.129
  155.71   251.8  342.26  426.05  622.03 1106.16
River Rch & RM=17417,36,9070.235
  159.14  257.41  349.95  435.68  636.09 1127.94
River Rch & RM=17417,36,8922.341
  164.06  265.46  360.99  449.52  656.29  1159.1
River Rch & RM=17417,36,8774.446
  167.82  271.62  369.44   460.1  671.75 1182.85
River Rch & RM=17417,36,8626.552
  169.32  274.08  372.81  464.32  677.91  1192.3
River Rch & RM=17417,36,8478.657
  263.03  427.18  582.54  726.72 1061.01 1757.17
River Rch & RM=17417,36,8330.763
  267.11  433.87  591.74  738.26 1077.85 1781.41
River Rch & RM=17417,36,8182.869
   270.5  439.43  599.38  747.84 1091.85 1801.51
River Rch & RM=17417,36,8034.975
  272.86  443.31  604.71  754.54 1101.62 1815.53
River Rch & RM=17417,36, 7887.08
  277.57  451.05  615.35  767.88 1121.11 1843.43
River Rch & RM=17417,36,7739.186
  285.26  463.69  632.73   789.7 1152.96 1888.92
River Rch & RM=17417,36,7591.292
  296.24  481.72  657.52  820.81 1198.38 1953.45
River Rch & RM=17417,36,7443.397
  297.23  483.35  659.77  823.62 1202.49 1959.27
River Rch & RM=17417,36,7295.503
  306.79  499.06  681.37  850.74 1242.07 2015.23
River Rch & RM=17417,36,7222.226
  309.41  503.36   687.3  858.17 1252.93 2030.56
River Rch & RM=17417,36,7074.983
   314.3   511.4  698.36  872.08 1273.23 2059.18
River Rch & RM=17417,36,6927.741
  320.13  521.01  711.59   888.7  1297.5 2093.32
River Rch & RM=17417,36,6780.498
  324.65  528.44  721.83  901.57 1316.29 2119.72
River Rch & RM=17417,36,6633.255
  325.61  530.03  724.02  904.32 1320.31 2125.37
River Rch & RM=17417,36,6486.012
  326.25  531.09  725.48  906.16 1322.99 2129.12
River Rch & RM=17417,36,6338.769
  343.88  560.11  765.45  956.37  1396.3 2231.46
River Rch & RM=17417,36,6155.413
     348   566.9  774.81  968.14 1413.49 2255.38
River Rch & RM=17417,36,6044.283
   349.9  570.03  779.13  973.57 1421.41 2266.38
River Rch & RM=17417,36, 5897.04
  352.75  574.72  785.59   981.7 1433.27 2282.85
River Rch & RM=17417,36,5749.797
  357.17  582.02  795.64  994.32 1451.71 2308.38
River Rch & RM=17417,36,5602.555
  360.64  587.73  803.51 1004.21 1466.15 2328.36
River Rch & RM=17417,36,5455.312
  363.16  591.88  809.23  1011.4 1476.65 2342.84
River Rch & RM=17417,36,5308.342
  365.36  595.51  814.23 1017.68 1485.82 2355.49
Boundary for River Rch & Prof#=17417,36,1
Up Type= 0
Dn Type= 2
Boundary for River Rch & Prof#=17417,36,2
Up Type= 0
Dn Type= 2
Boundary for River Rch & Prof#=17417,36,2
Up Type= 0
Dn Type= 2
Boundary for River Rch & Prof#=17417,36,2
Up Type= 0
Dn Type= 2
Boundary for River Rch & Prof#=17417,36,2
Up Type= 0
Dn Type= 2
Boundary for River Rch & Prof#=17417,36,2
Up Type= 0
Dn Type= 2

--- 17417_ras.g01 (geometry) ---

Geom Title=17417
Program Version=4.10

River Reach=17417,36
Reach XY= 30
816344.075452358785995.781133682816529.191409856786051.637497082
816659.242212325786357.948384166816820.328448325786462.003824681
816826.942846417786573.771738917817098.260322392786788.888372451
817289.331162721787404.071676388 817357.93840909787533.053299516
 817548.26356259787640.986907884 817650.22701624787773.148967192
817856.987569958787788.752017662817809.412318408787867.594192207
817867.935910314787962.467835918817842.262443393788107.349003226
817725.718700081788114.318821415817651.570579737788216.234163731
817539.480926365788232.065440565817482.462194473788493.174671456
817435.876240939788529.230516389817413.373064131788464.465275839
 817367.26899457788463.367559895817292.594526827 788804.91822575
816817.573919028789023.857286781815926.541632712789561.650426641
815191.917883635789936.006468713814478.048022658 790436.48773253
  814092.4974069790787.942314863813886.699125201790853.750397265
813430.467300624790903.897413328812828.444655001790862.464288473

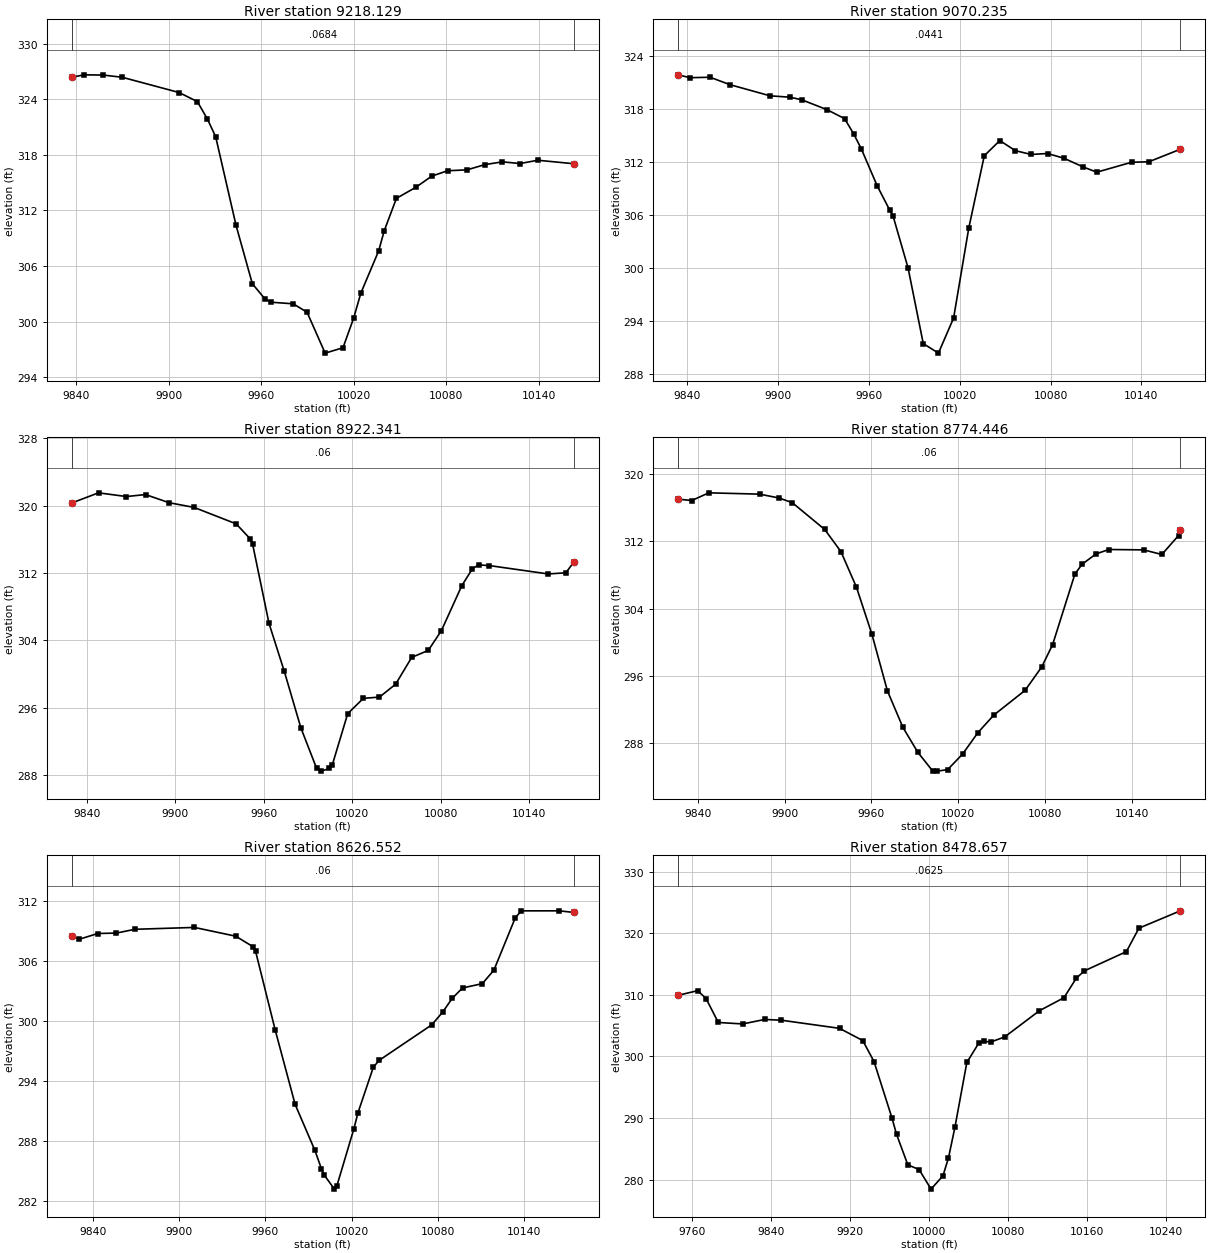
Type RM Length L Ch R = 1 ,9218.129,147.894300,147.894300,147.894300
XS GIS Cut Line= 6
816254.684384173786131.583655613 816293.23391951786077.835161478
  816334.6070359786013.312338525816345.447028952785995.436492353
816364.031934821785963.626083184 816424.85128753785854.574289708
#Sta/Elev= 30
9837.303326.38429845.404326.64439857.711326.61919870.017326.37989906.814 324.736
9918.693323.75629925.244321.85659930.572319.9615 9943.77310.39479954.331304.0912
9962.296302.4946 9966.21302.09889980.851 301.9239989.819301.009910001.51 296.599
10013.09297.180710019.94300.349210024.67303.080210036.25307.656310039.83309.8177
10047.72313.309110060.36314.508210070.62315.708110080.89316.288410093.52316.3863
10104.97316.947910116.42317.250410127.87317.066710139.32 317.42210162.71317.0467
#Mann= 3 , 0 , 0
9837.303  0.0684       09837.303  0.0684       010162.71  0.0684       0
#XS Ineff= 2 , 0
       0                               0
Bank Sta=9837.303,10162.71
Exp/Cntr=0.3,0.1

Type RM Length L Ch R = 1 ,9070.235,147.894300,147.894300,147.894300
XS GIS Cut Line= 6
816402.355546815786180.845996071 816447.72651751786128.502462037
816473.309387407786089.839025327816480.466481793786067.146596693
816490.598012013785978.610724882816535.487004828 785886.88538391
#Sta/Elev= 30
9834.379321.87439842.115 321.5489855.349321.60069868.583320.7543 9895.05319.4927
 9908.01319.34259915.858319.04739932.522317.92639944.103316.9148 9950.08315.2021
9955.154313.49519965.639309.29779973.874306.55759976.023305.93359986.034299.9802
9996.045291.418310006.05  290.3410016.06294.316710026.07304.513410036.31312.7062
10046.55314.425710056.78313.281210067.22312.851210078.02 312.95810088.81312.4281
10101.59311.430810110.55310.842410133.45 311.966 10144.9312.024710165.64313.4406
#Mann= 3 , 0 , 0
9834.379  0.0441       09834.379  0.0441       010165.64  0.0441       0
#XS Ineff= 2 , 0
       0                               0
Bank Sta=9834.379,10165.64
Exp/Cntr=0.3,0.1

Type RM Length L Ch R = 1 ,8922.341,147.894300,147.894300,147.894300
XS GIS Cut Line= 6
816406.536305918786236.583440316816457.224828447 786194.48510508
816494.498603058786169.379061476816522.402455383786155.701204441
816608.176481144786122.914504566816699.536432698786068.551209539
#Sta/Elev= 30
9829.914320.30519848.044321.50969866.914321.06879879.913321.30259895.805320.3399
9912.783 319.7799941.303317.82759950.694 316.072 9952.44315.42179963.577306.0032
9973.915300.3211 9985.19293.59279995.802288.8099    9999288.473510004.52288.7919
10006.33289.1436 10016.9295.297510027.51297.114710038.43297.262310049.35298.7928
10060.26301.974710071.49302.806310080.38305.151810094.22310.493110101.43312.5057
10105.58312.952610112.77312.875610152.83311.878210164.72312.019110170.12313.3017
#Mann= 3 , 0 , 0
9829.914    0.06       09829.914    0.06       010170.12    0.06       0
#XS Ineff= 2 , 0
       0                               0
Bank Sta=9829.914,10170.12
Exp/Cntr=0.3,0.1

Type RM Length L Ch R = 1 ,8774.446,147.894300,147.894300,147.894300
XS GIS Cut Line= 6
816476.964312771786340.557562477816575.867516407786285.342744412
816615.067130697786270.532026715816660.094895663786259.152261181
816694.273436065786244.716221609816786.039400938786187.902943927
#Sta/Elev= 30
9826.571317.01639835.974316.85969847.675317.77299882.777317.61639896.346317.1531
9905.344316.60169927.753313.41349938.957310.78719949.692306.54549960.382300.9452
9971.072294.22229981.762289.88379992.062286.921410002.32284.696510005.63284.6764
10012.67284.855210023.02286.706910033.62289.258810044.48291.327210066.23294.2918
 10077.7297.073510085.22299.732210100.65308.144210105.63309.288510115.12310.5016
10124.01311.032910148.08310.987310160.66310.440310172.16312.690910173.41313.3485
#Mann= 3 , 0 , 0
9826.571    0.06       09826.571    0.06       010173.41    0.06       0
#XS Ineff= 2 , 0
       0                               0
Bank Sta=9826.571,10173.41
Exp/Cntr=0.3,0.1

Type RM Length L Ch R = 1 ,8626.552,147.894400,147.894400,147.894400
XS GIS Cut Line= 6
816570.952625899786510.195743652816616.506576745786472.881551847
816648.691640846 786443.53275056816752.448280751786332.015343497
816785.672993767786300.406449668816822.564318895 786268.17075735
#Sta/Elev= 30
9825.194308.54059830.426308.20439843.353308.77699856.279308.82149869.206309.1996
9910.618309.38589939.387308.50739951.358307.46029953.158307.01849966.929299.0731
9980.699291.6768 9994.47287.0666    9999285.2343   10001284.588810008.09283.1799
10009.74283.475810021.66289.233310024.54290.848710035.22295.401910039.34296.0873
10075.91299.635710083.48300.910610090.14302.289310097.29 303.32610111.09303.7561
10119.16305.114810134.04310.352110138.21311.045810164.77311.048410174.81310.8848
#Mann= 3 , 0 , 0
9825.194    0.06       09825.194    0.06       010174.81    0.06       0
#XS Ineff= 2 , 0
       0                               0
Bank Sta=9825.194,10174.81
Exp/Cntr=0.3,0.1

Type RM Length L Ch R = 1 ,8478.657,147.894300,147.894300,147.894300
XS GIS Cut Line= 6
816612.237162803786606.651419949816726.193529719786523.471435092
816761.883992791 786500.91027387816816.131958768786471.125654444
816886.729066536786423.071133118817028.029303061786315.101822895
#Sta/Elev= 30
 9745.79309.91419765.553310.66039773.972309.37499786.353305.49449811.114305.2568
9833.398305.9889 9850.36305.85899909.124 304.5449932.653302.55999944.062299.1503
9962.157290.03039966.878287.33829978.286282.38799989.694281.620110001.82278.4433
 10013.9 280.61910019.48283.524110025.98288.470210038.06299.003310050.14302.1466
10055.13302.439910062.22302.318210076.39303.149910111.53307.402710136.39309.5097
10148.84312.6631   10157313.867210199.62316.994810212.31320.803610254.24323.6189
#Mann= 3 , 0 , 0
 9745.79  0.0625       0 9745.79  0.0625       010254.24  0.0625       0
#XS Ineff= 2 , 0
       0                               0
Bank Sta=9745.79,10254.24
Exp/Cntr=0.3,0.1

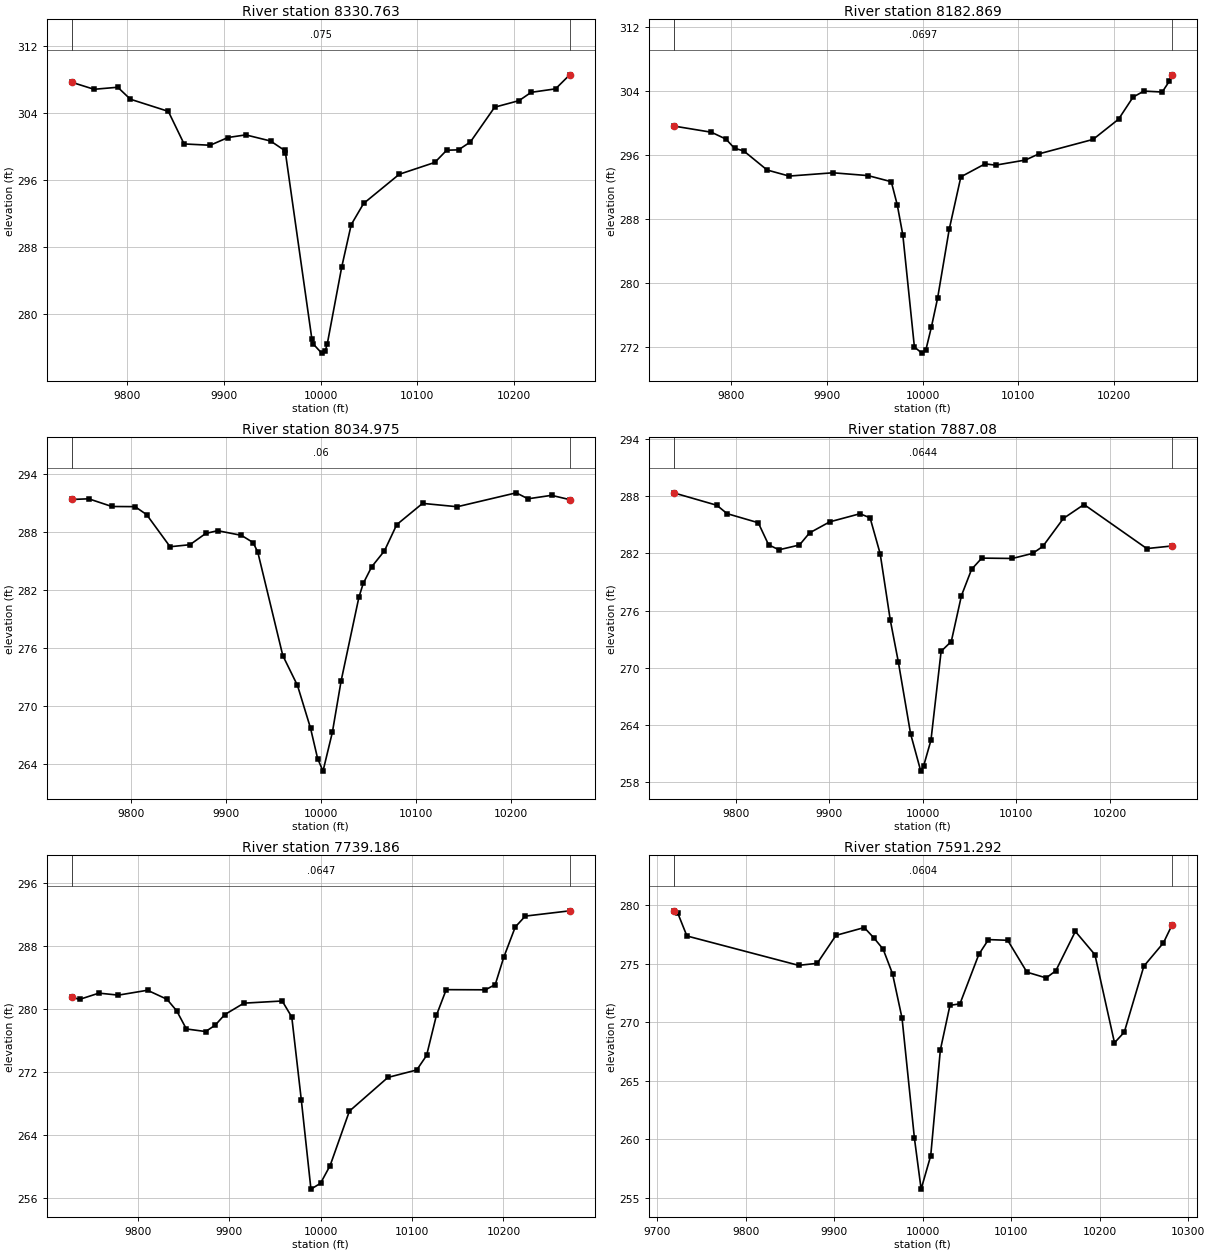
Type RM Length L Ch R = 1 ,8330.763,147.894300,147.894300,147.894300
XS GIS Cut Line= 6
816658.485990922786769.991563543816768.092116168786677.592312513
816852.307097932786598.935691368816879.616806749786574.219557742
816978.310853888 786504.02536519817056.610434084786444.036896844
#Sta/Elev= 30
9742.409307.65569765.668306.81229790.166307.05529803.245305.62739842.483304.1807
9858.757300.29789885.765300.14239904.217301.06569922.578301.37779948.176300.6486
9962.829299.51759963.622 299.2289990.984276.99569992.136 276.482   10001275.3631
10004.63275.581710006.87276.468410021.77285.613410031.61290.676610044.44293.2051
10081.25296.680310118.07298.094310130.34299.548810142.61299.593410154.88300.5345
10179.97 304.67910205.16305.459710217.76306.450710242.96306.864310257.58308.5363
#Mann= 3 , 0 , 0
9742.409   0.075       09742.409   0.075       010257.58   0.075       0
#XS Ineff= 2 , 0
       0                               0
Bank Sta=9742.409,10257.58
Exp/Cntr=0.3,0.1

Type RM Length L Ch R = 1 ,8182.869,147.894300,147.894300,147.894300
XS GIS Cut Line= 6
816797.258147238 786881.02367523816852.204555266786832.688078437
816900.935097593786781.650482079817033.507502733786604.079458034
817086.416497037786551.157473604817147.019605169786498.409270484
#Sta/Elev= 30
9739.652299.58769779.053298.81079794.193297.95869803.238296.80599812.833296.4782
9837.289 294.0899860.324293.33059906.107293.74179942.819293.38939967.091292.6242
9973.364289.7145 9979.17285.95589991.248271.9614    9999271.193110003.32 271.636
10008.95 274.41710015.49278.059210027.66286.680510039.82293.233610065.09 294.857
 10076.1294.696610107.29 295.33610121.43296.107810178.01297.914110204.65300.4406
10219.85303.209110231.16 303.95410250.32303.842210257.68 305.18510260.36305.9898
#Mann= 3 , 0 , 0
9739.652  0.0697       09739.652  0.0697       010260.36  0.0697       0
#XS Ineff= 2 , 0
       0                               0
Bank Sta=9739.652,10260.36
Exp/Cntr=0.3,0.1

Type RM Length L Ch R = 1 ,8034.975,147.894300,147.894300,147.894300
XS GIS Cut Line= 6
816880.208903654786937.362034744817038.755827335786822.030798213
 817072.69107654786793.311856043817101.030225314 786760.54398988
817137.853970567786727.509256114817290.444790378786612.228657391
#Sta/Elev= 30
9737.694291.39539755.741291.46599780.144290.66979804.546290.65429816.748289.8281
9841.447286.50199862.358286.7117 9878.98287.87729891.523288.16489916.561287.6815
9928.846286.93729933.781285.95279960.145275.23189975.625272.1317 9989.34267.7174
9996.806264.570810002.49263.263310012.34267.280110021.57272.608610040.34281.2871
10044.85282.697210053.77284.425710067.21286.077310080.15288.792410107.36290.9918
10143.86290.644710205.98292.085110218.37291.465610243.17291.825810262.31291.3806
#Mann= 3 , 0 , 0
9737.694    0.06       09737.694    0.06       010262.31    0.06       0
#XS Ineff= 2 , 0
       0                               0
Bank Sta=9737.694,10262.31
Exp/Cntr=0.3,0.1

Type RM Length L Ch R = 1 , 7887.08,147.894300,147.894300,147.894300
XS GIS Cut Line= 6
816903.434410756 787018.15885384817016.568379268786964.257511593
817122.960673025786921.299916884817269.011924776786858.982932632
817320.007063816786835.141243825817388.854990515786799.972562385
#Sta/Elev= 30
9733.781288.34039779.824287.03899790.901286.15769824.131285.20649835.208282.8909
9846.285282.36879868.193282.87269878.977 284.1399900.546285.29789932.899 286.149
9943.683285.71929954.468281.95659965.252275.01459973.837270.64019986.961263.0924
9997.861259.1706   10001259.741810008.75262.410110019.61271.729910030.48272.7567
10041.34277.565810052.21280.328110063.08281.497410095.67281.4609 10117.4 281.991
10128.27282.718610150.28285.654510172.36287.116810239.44282.497110266.23282.7688
#Mann= 3 , 0 , 0
9733.781  0.0644       09733.781  0.0644       010266.23  0.0644       0
#XS Ineff= 2 , 0
       0                               0
Bank Sta=9733.781,10266.23
Exp/Cntr=0.3,0.1

Type RM Length L Ch R = 1 ,7739.186,147.894300,147.894300,147.894300
XS GIS Cut Line= 6
816926.834658511787139.696432117817050.674840758 787095.06139341
817184.185303264787053.252109526817284.203346383787020.246104252
817367.493486042786987.705593588817439.293272802786955.259781497
#Sta/Elev= 30
9727.458281.56549736.137281.27229757.397282.06889778.656281.81469810.545282.4341
9831.805281.29229842.434279.82879853.064277.51599874.107277.19049884.586  277.99
9895.065279.33799916.023280.79449957.938281.06949968.417 279.0319978.896268.4438
9989.375257.16569999.865257.9064 10010.4260.167310031.46267.074910073.58 271.357
10105.18272.307810115.92274.150410126.65279.234210137.39282.509610180.33282.4904
10191.07283.159210200.32 286.60710212.96290.469810223.93291.855610272.54292.5259
#Mann= 3 , 0 , 0
9727.458  0.0647       09727.458  0.0647       010272.54  0.0647       0
#XS Ineff= 2 , 0
       0                               0
Bank Sta=9727.458,10272.54
Exp/Cntr=0.3,0.1

Type RM Length L Ch R = 1 ,7591.292,147.894400,147.894400,147.894400
XS GIS Cut Line= 6
816970.823679933787283.621394067817127.612755269787232.570414385
817204.737429332  787204.3537778817237.666276315787191.108420778
817376.213563508787131.913552381817493.604213535787076.443283077
#Sta/Elev= 30
9718.492279.50679722.884279.34939733.401 277.3619859.602274.85419880.635275.0218
9901.897 277.4139933.842278.0785 9944.49277.21599955.138 276.243 9965.79274.1399
9976.568 270.3439990.576260.08399998.125255.753710008.98258.604910019.85267.6264
10030.72271.4399   10042271.567410063.35275.788510074.22277.051710095.97276.9913
10117.72274.270710139.47273.781210150.34274.387810172.44277.748910194.56275.7637
10216.68268.243810227.74 269.15110249.86274.782410271.98276.7709 10281.5278.2658
#Mann= 3 , 0 , 0
9718.492  0.0604       09718.492  0.0604       0 10281.5  0.0604       0
#XS Ineff= 2 , 0
       0                               0
Bank Sta=9718.492,10281.5
Exp/Cntr=0.3,0.1

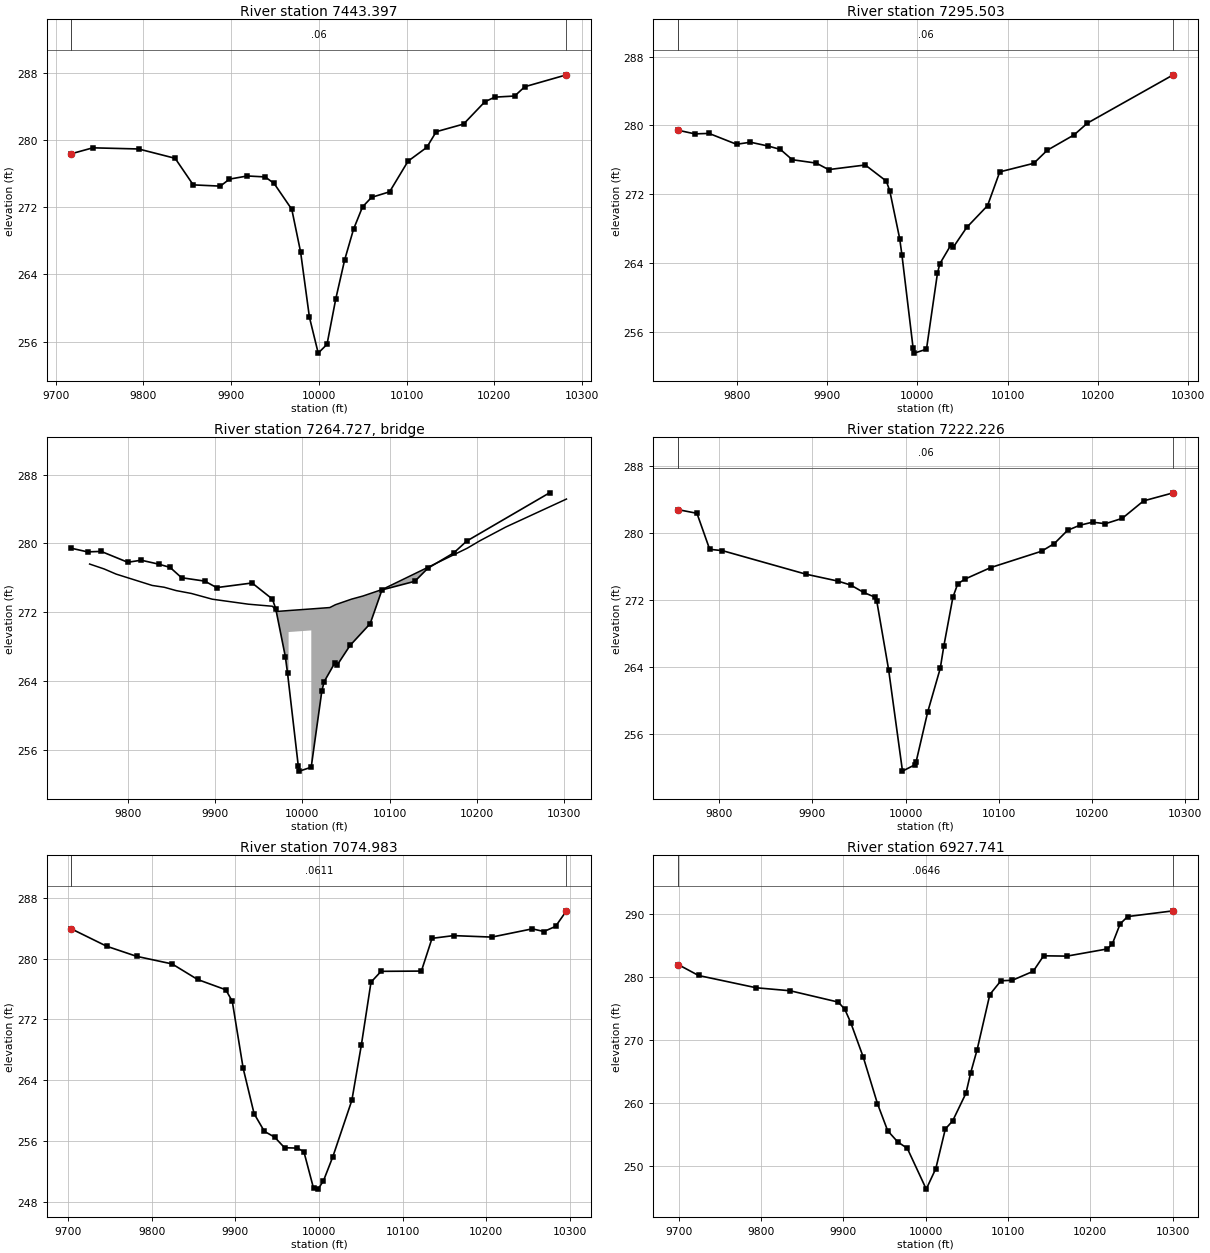
Type RM Length L Ch R = 1 ,7443.397,147.894300,147.894300,147.894300
XS GIS Cut Line= 6
817011.496755947787393.409325091817190.409444013787343.310464095
817323.407873831787325.756545707 817371.99892141787314.017489223
817448.083281778 787282.85835939817545.943333566787228.132776554
#Sta/Elev= 30
9717.716278.36919742.241279.07439794.413278.93859836.093277.82669856.719274.6623
9887.659274.51459897.972275.34539918.376275.72359938.697275.61019948.858274.8409
9969.094271.75079979.132266.67289989.171258.92199999.208254.632310009.26255.6852
10019.31261.129110029.37265.732410039.46269.377210049.75272.045110060.03273.1775
10080.61273.838610101.65277.488810122.94279.124110133.76280.9937 10164.9281.9009
10189.22284.559210200.54285.108910223.16285.241810234.75286.349410282.24287.7652
#Mann= 3 , 0 , 0
9717.716    0.06       09717.716    0.06       010282.24    0.06       0
#XS Ineff= 2 , 0
       0                               0
Bank Sta=9717.716,10282.24
Exp/Cntr=0.3,0.1

Type RM Length L Ch R = 1 ,7295.503,73.276700,73.276700,73.276700
XS GIS Cut Line= 6
817118.951980233787647.082967669817226.422787637787555.149557397
817333.970364392787456.772704199817488.110890299787316.557646364
817499.732500106787302.611714587817524.125031829787278.142562047
#Sta/Elev= 30
9735.194279.42859753.783279.00459769.473 279.0589799.934277.79499815.317278.0353
9835.271277.5803 9848.43277.1991 9861.59275.99959888.246275.60319901.799274.8488
9942.457275.38639965.739273.51239969.562272.38779980.555266.82289983.114264.8697
9995.371254.12729996.667253.502210010.22253.957410022.38262.794210025.01263.8972
10037.29 266.08810039.87265.816810054.73268.115910077.84270.657410091.36274.5837
10129.04275.5824 10143.9277.097610173.62 278.88510188.48280.260310283.45285.8734
#Mann= 3 , 0 , 0
9735.194    0.06       09735.194    0.06       010283.45    0.06       0
#XS Ineff= 2 , 0
       0                               0
Bank Sta=9735.194,10283.45
Exp/Cntr=0.3,0.1

Type RM Length L Ch R = 3 ,7264.727,,,
BEGIN DESCRIPTION:
END DESCRIPTION:
Bridge Culvert--1,0,-1,-1, 0
Deck Dist Width WeirC Skew NumUp NumDn MinLoCord MaxHiCord MaxSubmerge Is_Ogee
20.638350,32.000000,2.6,0, 25, 25, , , 0.95, 0, 0,0,,
 9756.19 9772.79 9786.57 9827.92 9841.70 9855.48 9872.75 9896.83 9938.18 9965.75
 9968.65 9970.13 9984.31 9984.3110010.3110010.3110031.5510037.9810056.5110069.48
10091.8710189.0610203.8310233.3810302.84
  277.59  277.02  276.42  275.10  274.89  274.50  274.17  273.50  272.92  272.68
  272.36  272.07  272.18  272.18  272.37  272.37  272.53  272.86  273.51  273.87
  274.64  279.43  280.31  281.90  285.15
 -722.41 -722.98 -723.58 -724.90 -725.11 -725.50 -725.83 -726.50 -727.08 -727.32
 -727.64 -727.93 -727.82  269.68  269.87 -727.63 -727.47 -727.14 -726.49 -726.13
 -725.36 -720.57 -719.69 -718.10 -714.85
 9756.19 9772.79 9786.57 9827.92 9841.70 9855.48 9872.75 9896.83 9938.18 9965.75
 9968.65 9970.13 9983.99 9983.9910009.9910009.9910031.5510037.9810056.5110069.48
10091.8710189.0610203.8310233.3810302.84
  277.59  277.02  276.42  275.10  274.89  274.50  274.17  273.50  272.92  272.68
  272.36  272.07  272.18  272.18  272.37  272.37  272.53  272.86  273.51  273.87
  274.64  279.43  280.31  281.90  285.15
 -722.41 -722.98 -723.58 -724.90 -725.11 -725.50 -725.83 -726.50 -727.08 -727.32
 -727.64 -727.93 -727.82  269.68  269.87 -727.63 -727.47 -727.14 -726.49 -726.13
 -725.36 -720.57 -719.69 -718.10 -714.85
BR Coef=-1 , 0 , 0 ,, 0 ,,,0.8,0,1,0,
WSPro=,,,, 1 ,,,, 0 ,,,, 0 ,,,,-1 ,-1 ,-1 , 0 , 0 , 0 , 0 , 0
BC Design=,, 0 ,, 0 ,,,,,,

Type RM Length L Ch R = 1 ,7222.226,147.242900,147.242900,147.242900
XS GIS Cut Line= 5
817180.159270138787700.355979249817280.687445909787607.027722552
 817347.41564396787541.766078308817426.646755368787469.737795174
817568.302378863787337.685942784
#Sta/Elev= 30
9755.798282.82589776.049 282.3879789.694278.07559803.339277.9178 9892.97275.0991
9926.977274.27929940.965273.80039954.953272.9092 9967.38272.3291 9968.94271.8928
9981.682263.66549996.557251.518310010.07252.290510011.23252.661310023.59258.5946
 10037.1263.836510040.96266.523510050.62272.323610055.83273.955210064.13274.5387
10091.16275.887410145.82277.849610159.49278.767910173.66280.349210186.83280.9588
 10200.5281.327110214.17281.138610232.32281.782910255.19 283.87410287.04284.8393
#Mann= 3 , 0 , 0
9755.798    0.06       09755.798    0.06       010287.04    0.06       0
#XS Ineff= 2 , 0
       0                               0
Bank Sta=9755.798,10287.04
Exp/Cntr=0.3,0.1

Type RM Length L Ch R = 1 ,7074.983,147.242800,147.242800,147.242800
XS GIS Cut Line= 6
817257.869039292787820.826611101 817339.72703057787770.796483232
817403.713020199787712.459481428817443.493535293787661.506722088
817533.312632129787512.775997379817647.118869033787385.628960392
#Sta/Elev= 30
9703.933283.92269746.345281.62699782.073280.30139824.488279.30149854.945 277.254
9888.662275.89889896.416274.38889909.489265.54419922.544259.5755 9934.81257.2532
9947.076256.49169958.903255.09729974.118255.04529982.084254.56949993.675249.7313
    9999249.643110005.41250.719410016.76253.932310039.45261.3437 10050.8268.6269
10062.34276.904210074.39278.326310122.59 278.361 10135.3282.670810161.08283.0316
 10206.8282.835910255.18283.9222 10269.1283.571810283.02284.244110296.07286.2954
#Mann= 3 , 0 , 0
9703.933  0.0611       09703.933  0.0611       010296.07  0.0611       0
#XS Ineff= 2 , 0
       09975.025                       0
Bank Sta=9703.933,10296.07
Exp/Cntr=0.3,0.1

Type RM Length L Ch R = 1 ,6927.741,147.242900,147.242900,147.242900
XS GIS Cut Line= 6
817340.589423791787866.394520186817422.671479027787818.828002611
817537.769200562787721.346807761817629.670221133787661.744219196
 817662.50780884787627.428065318817787.354361573787473.187896237
#Sta/Elev= 30
9699.198282.00079724.068280.25569794.206278.29999835.478277.8234 9893.73276.0242
9901.683274.90369908.986 272.7389924.243267.23629941.406259.86729953.834255.5472
 9965.95253.77999977.723252.7345 10000.7246.252410012.29249.511310023.89255.8238
10032.73257.101510048.92261.506610054.77264.802610062.48268.425810077.95277.2269
10091.41279.413110105.34279.495210130.64280.925810143.29  283.3910171.64283.3399
10220.61284.4813 10226.7285.250110236.25288.464610245.35 289.63410300.78290.5482
#Mann= 3 , 0 , 0
9699.198  0.0646       09699.198  0.0646       010300.78  0.0646       0
#XS Ineff= 2 , 0
       0                               0
Bank Sta=9699.198,10300.78
Exp/Cntr=0.3,0.1

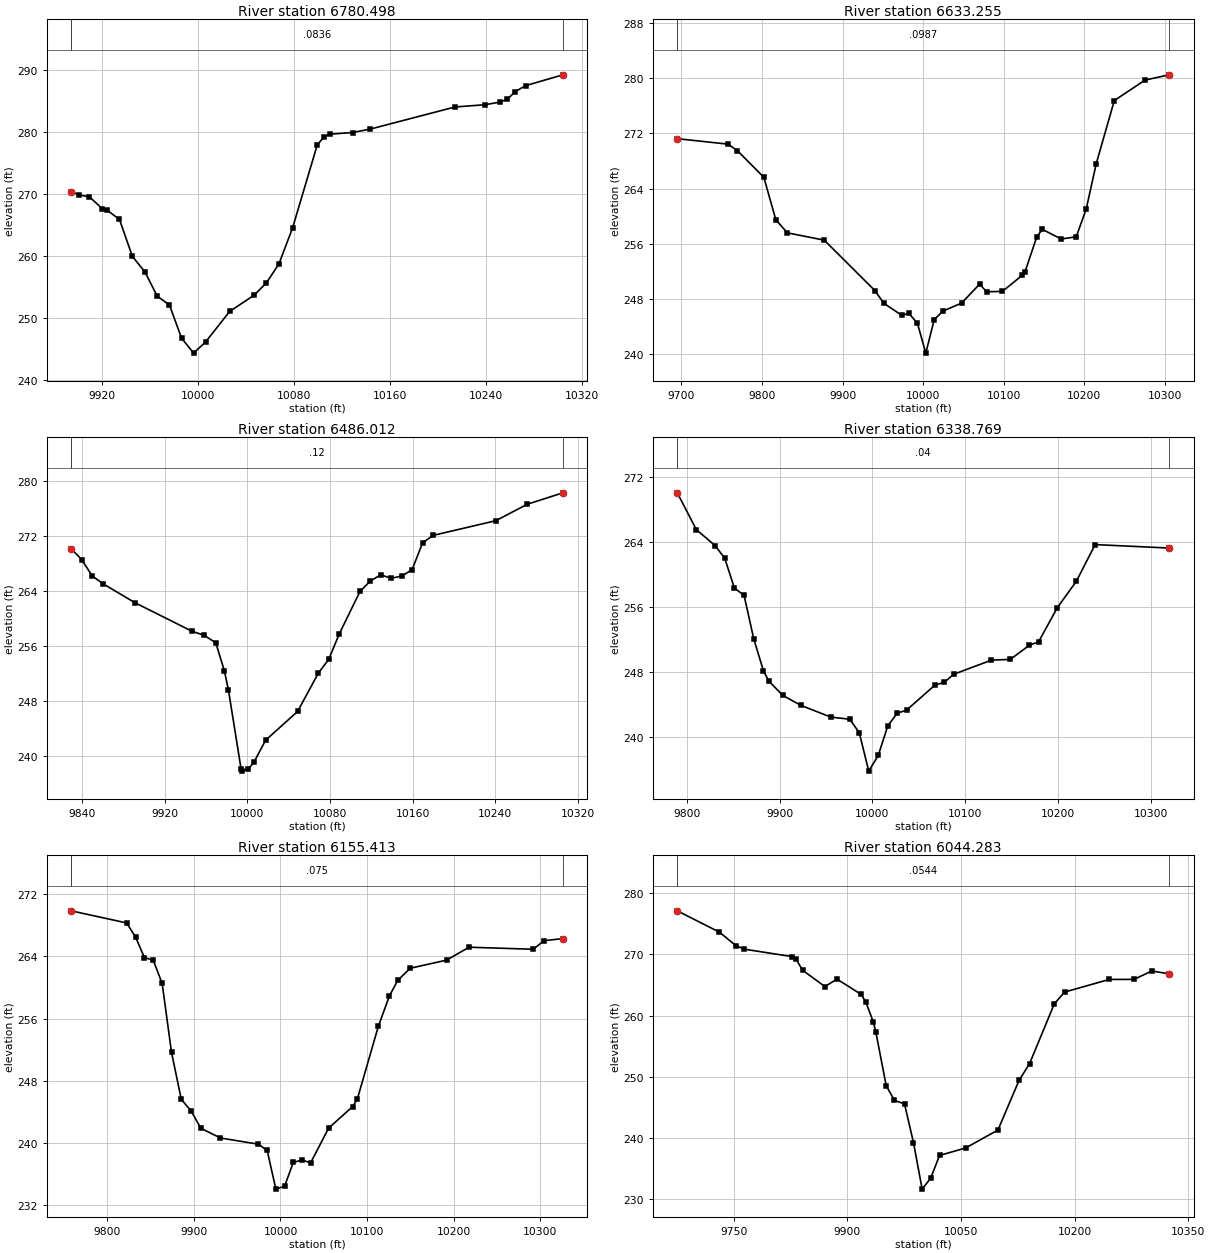
Type RM Length L Ch R = 1 ,6780.498,147.242900,147.242900,147.242900
XS GIS Cut Line= 6
817656.940839325787880.396163894817681.835891327787830.458803975
817696.833812623787731.679892295817719.208072722787669.382785072
817762.909737033787593.189973942817825.056862368787514.628598715
#Sta/Elev= 30
9893.977 270.3689900.329269.84349909.252269.52239920.092267.58719923.551267.4331
9934.324265.88029945.096259.90899955.577 257.4139965.816253.50029976.055252.0695
9986.117246.73129996.179244.298310006.23246.103310026.34251.036810046.65 253.639
10056.98255.6403 10067.4 258.68210078.88264.541610099.43277.914210105.22279.2323
10110.23 279.64310128.91279.903210143.76280.463210214.34284.027110239.08284.3852
10251.58 284.79710257.88285.238610264.68286.506910273.38287.471110304.44 289.216
#Mann= 3 , 0 , 0
9893.977  0.0836       09893.977  0.0836       010304.44  0.0836       0
#XS Ineff= 2 , 0
       0                               0
Bank Sta=9893.977,10304.44
Exp/Cntr=0.3,0.1

Type RM Length L Ch R = 1 ,6633.255,147.242900,147.242900,147.242900
XS GIS Cut Line= 6
817596.152470691787951.951277249  817668.3410788787923.049716871
817765.951561142787834.193490077817829.154756785787798.221008557
817892.597352589787689.374227945818049.915170189787567.867514121
#Sta/Elev= 30
9694.963271.21599757.709270.42859769.355269.50759802.343 265.6339817.197259.4971
 9831.46257.59449877.332 256.5389940.117249.2421 9951.29247.40149973.638245.6513
9982.081245.96569992.914244.525410003.31240.192610013.83245.051610024.76246.2793
10047.74247.432710070.11250.171310078.88249.065210098.48249.128910123.18251.4675
10126.52251.977810140.87256.948310147.86258.1014 10171.4 256.70410190.02257.0218
10202.44261.059910214.86267.6096 10237.3276.740210275.55279.701610305.21280.4554
#Mann= 3 , 0 , 0
9694.963  0.0987       09694.963  0.0987       010305.21  0.0987       0
#XS Ineff= 2 , 0
       0                10020.47       0
Bank Sta=9694.963,10305.21
Exp/Cntr=0.3,0.1

Type RM Length L Ch R = 1 ,6486.012,147.242900,147.242900,147.242900
XS GIS Cut Line= 6
817664.834546276787957.997500602817728.265735861787943.741065123
817758.634039974787930.428741636817845.109710251787878.899080551
817961.655202211787864.444986851818119.120883988787838.138162021
#Sta/Elev= 30
9829.255270.18939839.537268.58419849.662266.22349859.786 265.1249891.002262.3401
9946.399258.18759957.911257.60979969.424256.5239 9977.73252.42799981.621249.6996
9993.966238.15119994.784237.8753   10001238.175810006.39239.1864 10017.7242.3667
10048.65246.5399 10068.8252.112310078.88254.120710088.96257.781210109.11263.9649
10119.19265.500210129.26266.383210139.34265.882310149.44266.202810159.58267.1266
10169.71271.008610179.85272.109710240.68274.2438 10271.1276.630110305.69278.2937
#Mann= 3 , 0 , 0
9829.255    0.12       09829.255    0.12       010305.69    0.12       0
#XS Ineff= 2 , 0
       0                               0
Bank Sta=9829.255,10305.69
Exp/Cntr=0.3,0.1

Type RM Length L Ch R = 1 ,6338.769,183.356300,183.356300,183.356300
XS GIS Cut Line= 6
 817654.65976461787972.797183006817677.629274191787975.465433659
817709.138401794787982.628903991817787.779027875788006.191676678
817874.962872479788025.845042505818173.432861905788080.100699203
#Sta/Elev= 30
9789.679 270.0089810.156265.48819830.617263.49449840.872261.94339851.235258.2956
9861.674257.39159872.114252.04199882.553248.13169888.218246.86859903.431245.0849
9923.059243.86079955.113 242.4229975.614242.15739985.864240.50929996.114235.7735
10006.37237.707710016.62241.330110026.78 242.89810036.95243.278710067.44246.3543
 10077.6246.709110087.77 247.69310128.42249.424710148.75249.517910169.08251.2391
10179.24251.680410199.57255.9008 10219.9259.110610240.23263.641310319.94263.2157
#Mann= 3 , 0 , 0
9789.679    0.04       09789.679    0.04       010319.94    0.04       0
#XS Ineff= 2 , 0
       0                               0
Bank Sta=9789.679,10319.94
Exp/Cntr=0.3,0.1

Type RM Length L Ch R = 1 ,6155.413,111.129500,111.129500,111.129500
XS GIS Cut Line= 6
817572.572916061787993.929001912817744.626499236788052.864630356
817748.769822121788147.596695691817771.213254273788201.829414412
817837.514863223788275.025814533817943.292218477788351.665613517
#Sta/Elev= 30
9758.183269.86529822.269268.31019832.534 266.509  9842.8263.86679853.066263.5105
9863.331260.52649874.113251.67849885.413245.63929896.713244.15559908.014241.9237
9930.615240.67399974.514 239.8769984.605239.06579994.658234.101510004.72234.4777
10014.78237.5328 10024.8237.840810034.81237.478310055.52 241.93410083.38244.7168
10088.67 245.65610113.07255.0454 10125.7258.901210135.39260.926310149.82262.4859
 10191.9263.531210217.73265.1884 10292.1264.926610304.14266.023210326.15266.2989
#Mann= 3 , 0 , 0
9758.183   0.075       09758.183   0.075       010326.15   0.075       0
#XS Ineff= 2 , 0
       0                               0
Bank Sta=9758.183,10326.15
Exp/Cntr=0.3,0.1

Type RM Length L Ch R = 1 ,6044.283,31.803900,31.803900,31.803900
XS GIS Cut Line= 6
 817421.85486117 787994.07446364817493.782829803788018.046890252
817545.259020269788051.646029055817644.442510968788162.908023904
817713.746281055788207.364950802817923.522199115788391.865470999
#Sta/Elev= 30
9675.405 277.0869730.915273.61039752.734271.41169764.112270.82299826.679269.6207
 9831.87269.27159840.786267.39249870.278264.72869886.223265.93699918.115263.4555
 9924.32 262.1879934.036259.00989937.418257.38949951.247248.53749962.183246.1343
9975.405245.57919987.253239.26019998.695231.665210010.08233.474510021.63237.1626
10055.96238.374810098.77241.310210126.56249.394910140.46252.1281 10173.2261.9112
10186.82263.830710245.89265.891310278.42265.896210301.95267.2668 10324.7266.8079
#Mann= 3 , 0 , 0
9675.405  0.0544       09675.405  0.0544       0 10324.7  0.0544       0
#XS Ineff= 2 , 0
       0                               0
Bank Sta=9675.405,10324.7
Exp/Cntr=0.3,0.1

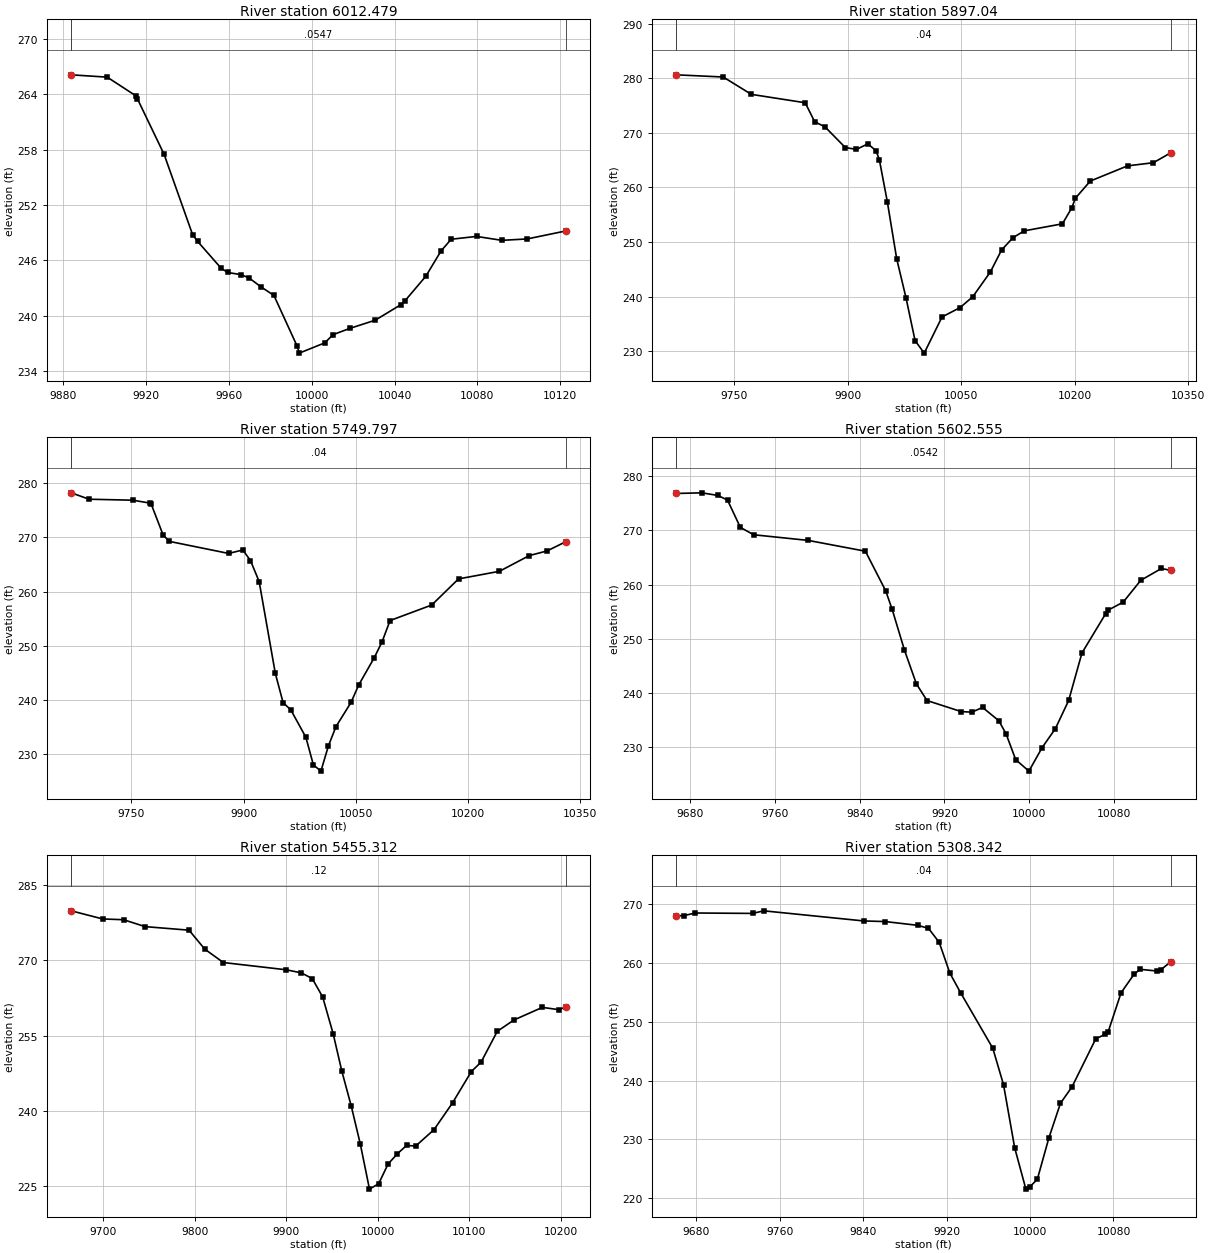
Type RM Length L Ch R = 1 ,6012.479,115.439000,115.439000,115.439000
XS GIS Cut Line= 3
817583.067630231788122.430258408817639.245649815788181.818450525
 817729.66550988788310.225352407
#Sta/Elev= 28
9883.886266.1334 9901.25265.88149914.954263.87739915.801263.54659928.719257.5088
9942.484248.79919944.905248.06629956.249245.15859959.457244.69279965.635244.4662
9969.526244.1382 9975.63243.11529981.757242.20569992.998236.68589993.987235.9452
10006.22237.050210010.37237.952310018.45238.630410030.68239.517310042.91241.1795
 10045.1 241.63310055.14244.292610062.47247.031810067.37248.2989 10079.6248.6047
10091.83248.179410104.06248.331610122.68249.1958
#Mann= 3 , 0 , 0
9883.886  0.0547       09883.886  0.0547       010122.68  0.0547       0
#XS Ineff= 2 , 0
       0                               0
Bank Sta=9883.886,10122.68
Exp/Cntr=0.3,0.1

Type RM Length L Ch R = 1 , 5897.04,147.242900,147.242900,147.242900
XS GIS Cut Line= 6
817292.481264015788034.890415415817377.998982989 788066.28463812
817452.966496673788113.921189076817512.389908033788173.030492126
817604.028205427788297.952874053817791.555426698788438.387628839
#Sta/Elev= 30
9673.093 280.6399735.078280.24029772.294277.06059843.487275.52399856.009272.0541
9869.754271.0998 9896.51267.32179911.158266.97839926.396267.99359937.188266.7323
9941.578265.07899952.075257.40949964.513246.93239976.878239.75069988.808231.9442
10000.91229.659410024.48236.287210048.26237.996110065.03239.975410088.44244.5434
 10103.2248.548610118.31250.813410133.35 252.06210183.65253.345710195.96 256.254
10200.84258.038710220.55261.181310269.73263.962110303.97264.540510326.98266.3626
#Mann= 3 , 0 , 0
9673.093    0.04       09673.093    0.04       010326.98    0.04       0
#XS Ineff= 2 , 0
       0                               0
Bank Sta=9673.093,10326.98
Exp/Cntr=0.3,0.1

Type RM Length L Ch R = 1 ,5749.797,147.242900,147.242900,147.242900
XS GIS Cut Line= 6
817234.601624706788209.183124121817444.436101208788345.782361004
 817480.56878474788358.641024517817619.479911336788384.307556547
817696.209802359788425.104020705817815.874833484 788503.55328248
#Sta/Elev= 30
9669.567278.19069693.388277.01399751.943276.83229774.802276.29779776.308276.1548
 9792.31270.43249800.674269.24519879.849267.02849898.881267.66379909.135265.7059
9920.705261.83979942.326244.92329952.727239.54029962.981238.22099983.124233.1757
9993.195228.078110003.26226.930410013.32231.599210023.37235.124710043.49239.5829
10053.73 242.79210074.41247.785510085.03 250.76310095.66254.663410151.37257.5264
10187.17262.332910241.91263.737710281.59266.623310305.51 267.48710330.47269.1789
#Mann= 3 , 0 , 0
9669.567    0.04       09669.567    0.04       010330.47    0.04       0
#XS Ineff= 2 , 0
       0                               0
Bank Sta=9669.567,10330.47
Exp/Cntr=0.3,0.1

Type RM Length L Ch R = 1 ,5602.555,147.242800,147.242800,147.242800
XS GIS Cut Line= 6
 817275.09458154 788252.95556155817358.359060544788312.612567006
817417.602605934788369.666584545817444.212966488788413.940115054
817465.458722606788493.520695265817582.061069396788582.012976153
#Sta/Elev= 30
9666.929276.82259691.019276.9392 9706.07276.45839715.223275.60059727.356270.5575
9739.959269.19679791.537268.15139845.396266.15999864.467258.88019870.613255.4534
9882.283 247.8859893.514241.67389903.554238.59069935.865236.55169945.928236.4446
9955.992237.32339971.374234.85719978.233232.40939987.265227.67849999.731225.5597
10012.25229.915610024.76233.416210037.27238.613410049.78 247.36810072.05254.5827
10074.79255.3108 10088.7256.753610105.34260.789610124.83262.973310133.66262.6256
#Mann= 3 , 0 , 0
9666.929  0.0542       09666.929  0.0542       010133.66  0.0542       0
#XS Ineff= 2 , 0
       0                               0
Bank Sta=9666.929,10133.66
Exp/Cntr=0.3,0.1

Type RM Length L Ch R = 1 ,5455.312,146.970100,146.970100,146.970100
XS GIS Cut Line= 6
 817174.96828696788225.359940962817299.299008603788301.608871351
817369.299746895788366.430956298817393.718952259788420.269614497
817391.712673271788546.973583865817453.102444901788638.102824264
#Sta/Elev= 30
9664.928279.89589699.271278.27549722.141278.12019745.682276.74369793.722276.0346
9810.895272.24959831.241269.57739900.171268.12789916.619267.50929928.405266.3723
 9939.78262.72549951.298255.34299960.816 247.8569970.951241.01189980.956233.3545
9990.982224.367310001.04225.454110011.23229.356210021.43231.419410031.52233.0784
10041.53232.969310061.55236.238910081.75241.567810102.36247.833310112.98249.7013
10130.68255.847110148.88258.112510179.98260.629810197.83260.179610205.53260.6714
#Mann= 3 , 0 , 0
9664.928    0.12       09664.928    0.12       010205.53    0.12       0
#XS Ineff= 2 , 0
       0                10172.42       0
Bank Sta=9664.928,10205.53
Exp/Cntr=0.3,0.1

Type RM Length L Ch R = 1 ,5308.342,143.805700,143.805700,143.805700
XS GIS Cut Line= 6
817008.666242127788463.101880329817132.946536681 788516.84817518
817305.199725532788562.925972973817327.673106819788571.627285065
 817391.44926873788604.178737509817442.530458004788643.388817712
#Sta/Elev= 30
9660.939268.10779667.927268.0759 9678.96268.54019734.024268.46949744.788  268.91
9840.413267.19129861.346267.07939892.374266.43949902.652265.9331 9912.93263.5507
9923.208 258.2919933.486254.96229964.321 245.5259974.599239.32879985.318 228.575
9996.045221.54749999.644 221.90910007.01223.219910018.09230.261210029.17236.1509
10040.25238.948910063.09247.144410071.96247.873310074.96248.339310087.34254.9792
10099.76 258.11510105.49258.954510121.52  258.6710125.34258.869310134.97260.2394
#Mann= 3 , 0 , 0
9660.939    0.04       09660.939    0.04       010134.97    0.04       0
#XS Ineff= 2 , 0
       0                10107.14       0
Bank Sta=9660.939,10134.97
Exp/Cntr=0.3,0.1