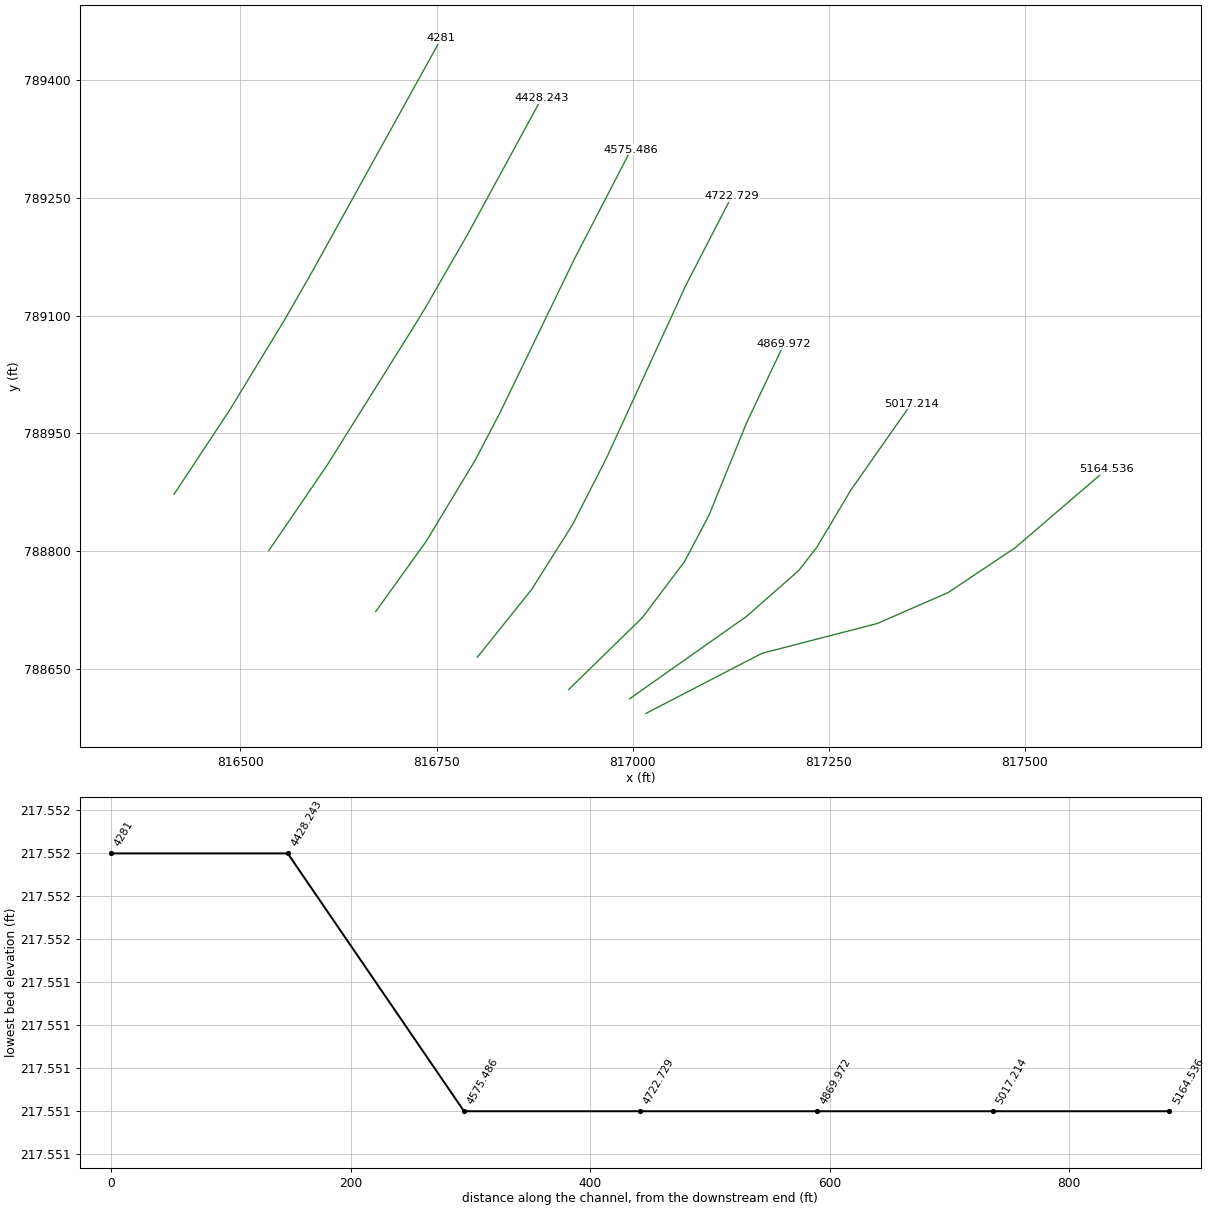
HEC-RAS study 17417_ras.prj: 17417

--- 17417_ras.g01 (geometry) --- (continued)

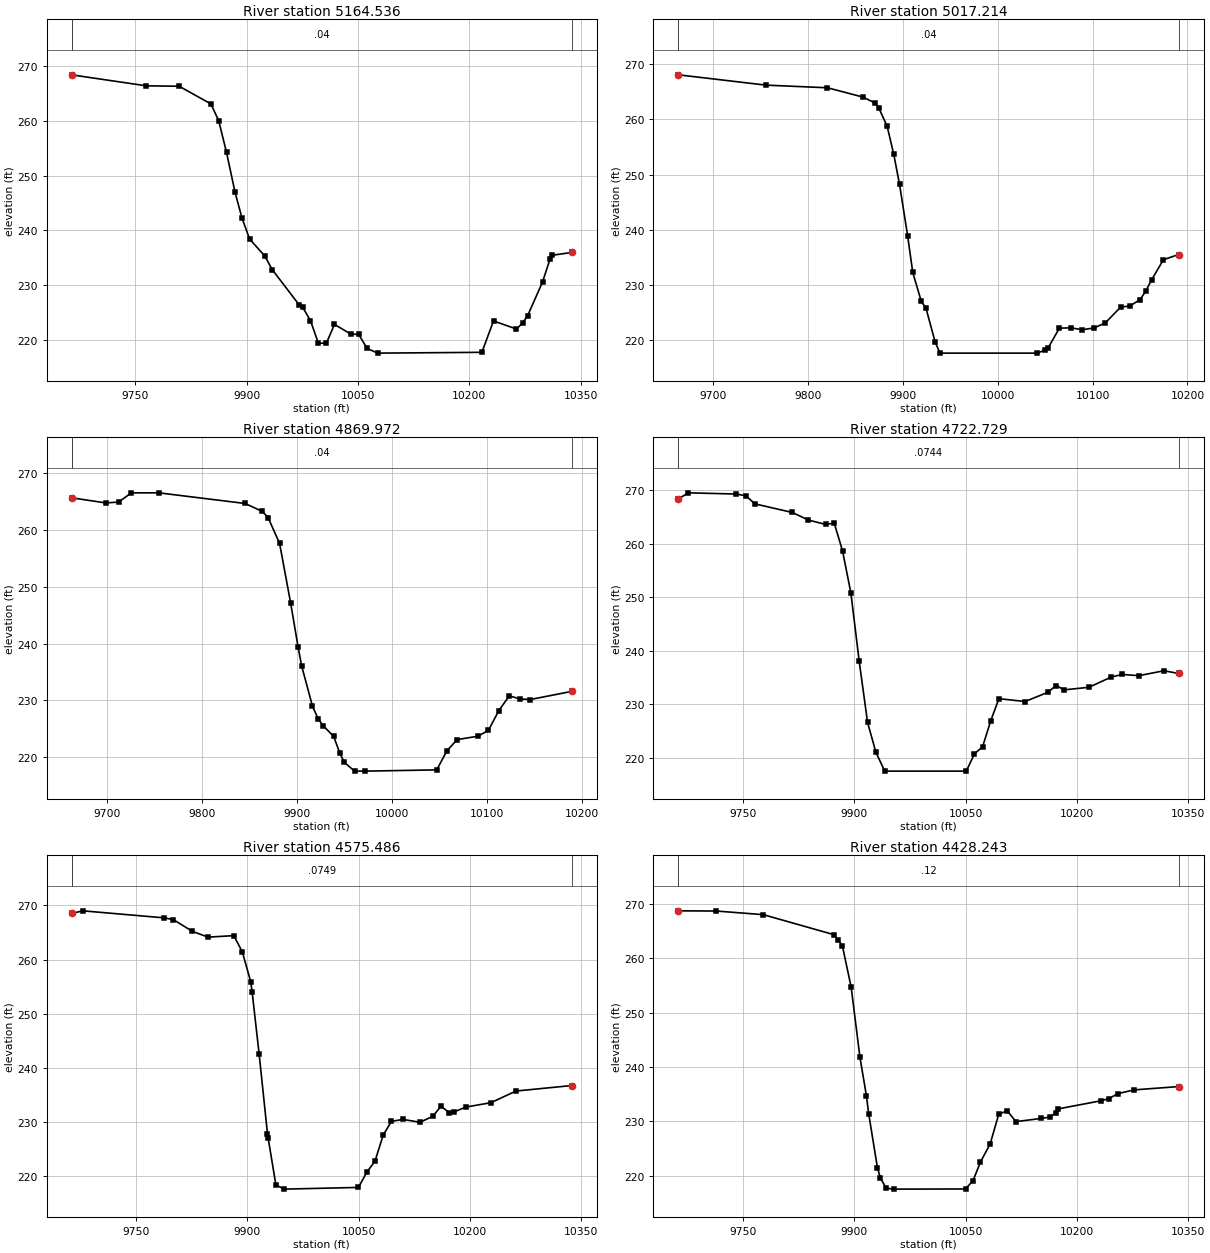
Type RM Length L Ch R = 1 ,5164.536,147.321500,147.321500,147.321500
XS GIS Cut Line= 6
817017.089664353788593.028975364817164.974373225788669.611680652
817311.997414429788707.615508454817402.383049607788747.134749919
817487.462923177788803.976206208817604.375273716788904.270477346
#Sta/Elev= 30
9664.063268.42029764.906266.4079  9809.1266.33259851.869263.10139862.394260.0264
 9872.92254.22949884.429246.92549893.714242.26269903.956238.4188 9924.44235.3048
9934.683232.78119970.721226.38529975.652225.90529986.028223.49459996.718219.3563
10007.53219.3799 10018.4222.801910040.13221.047810051.13 220.96710062.23218.4125
10076.59217.550810217.01217.698110232.75223.435510263.64221.953910272.07223.0829
10278.73224.402910298.77230.544710308.91234.760110312.12235.442910337.99235.9556
#Mann= 3 , 0 , 0
9664.063    0.04       09664.063    0.04       010337.99    0.04       0
#XS Ineff= 2 , 0
       0                 10022.1       0
Bank Sta=9664.063,10337.99
Exp/Cntr=0.3,0.1

Type RM Length L Ch R = 1 ,5017.214,147.242800,147.242800,147.242800
XS GIS Cut Line= 6
816996.492144185788611.805991434817145.342137475788716.770439109
817211.840796566788775.162895091817234.883027942788804.814089547
817278.197560829788877.648448414817355.321543097788987.797196235
#Sta/Elev= 30
9663.038268.11089755.341266.23929820.283265.75889857.568264.07549870.401262.9987
9874.262262.14129883.234258.74999890.219253.64539896.256248.22049904.915238.7669
9910.233232.21749919.228226.94859924.211225.69559933.773219.61499938.922217.5508
10041.38217.550810049.78218.100610052.99 218.49310064.94222.0916   10077222.1395
10089.07221.805310101.13222.1128 10113.2223.019210129.49 225.90810139.18226.1192
10149.93 227.24710156.13228.849110162.31230.9204 10174.7234.526210190.56235.4584
#Mann= 3 , 0 , 0
9663.038    0.04       09663.038    0.04       010190.56    0.04       0
#XS Ineff= 2 , 0
       0                10050.75       0
Bank Sta=9663.038,10190.56
Exp/Cntr=0.3,0.1

Type RM Length L Ch R = 1 ,4869.972,147.242900,147.242900,147.242900
XS GIS Cut Line= 6
816918.605518109788623.516744422817012.438280118788715.105934069
817066.024542416788786.299059624817097.162588831788845.107266754
817145.241020105788963.282510857 817192.97378502789063.897707822
#Sta/Elev= 30
 9663.02265.68779698.832 264.789  9712.4264.92599725.969266.5562 9754.72266.5623
9845.581264.68439863.742 263.2749869.742262.19889881.822 257.6439893.443247.1576
9901.317239.36319904.995236.09029916.395228.9789 9922.49226.74359927.547225.5576
9938.699223.66329945.084220.7421 9949.85219.09629960.681217.55719971.508217.5508
10047.07  217.7710057.85221.153210068.63223.107610090.43223.699410101.43224.7324
10112.42228.219310123.42230.811610134.41230.2713 10145.4230.159210188.94231.5893
#Mann= 3 , 0 , 0
 9663.02    0.04       0 9663.02    0.04       010188.94    0.04       0
#XS Ineff= 2 , 0
       0                               0
Bank Sta=9663.02,10188.94
Exp/Cntr=0.3,0.1

Type RM Length L Ch R = 1 ,4722.729,147.242900,147.242900,147.242900
XS GIS Cut Line= 6
816802.067147388788664.625316335816871.281813646788750.970351295
816923.594958969788833.943009515 816967.46712288788920.143694125
817067.915714697789138.766847856 817126.48893041789252.438306363
#Sta/Elev= 30
    9663268.33779676.564269.46199741.247269.23469753.745268.90939766.244267.3983
  9816.6265.79429838.256264.38219861.455263.56749873.015263.81339884.236258.6114
9895.456250.77859906.677238.02239917.898 226.6539929.118221.08399941.066217.5508
   10051217.5508   10062220.7741   10073222.1059   10084226.9761   10095231.0691
10130.15 230.531   10161232.2548   10172233.5214   10183232.713110216.16233.1842
10246.45235.105410261.16235.579510283.66  235.3610317.41 236.27310337.02235.7681
#Mann= 3 , 0 , 0
    9663  0.0744       0    9663  0.0744       010337.02  0.0744       0
#XS Ineff= 2 , 0
       0                               0
Bank Sta=9663,10337.02
Exp/Cntr=0.3,0.1

Type RM Length L Ch R = 1 ,4575.486,147.242900,147.242900,147.242900
XS GIS Cut Line= 6
816672.490382846788722.816602644 816737.08790442 788812.70195673
816799.187124199788915.592346894816830.828685515788976.083620647
816925.799912297789172.334953394816997.915818585 789311.61784174
#Sta/Elev= 30
9662.979268.52279678.172269.01399788.244267.71059800.077267.39599825.892265.2139
9846.993264.15339881.654264.42359893.207261.41519904.509255.87149906.433253.9581
9915.794242.5691 9927.08227.77999928.008226.98869938.365218.34059949.583217.5508
10049.72217.864510060.84220.661910071.96 222.71410083.08227.5521 10094.2230.0806
10109.73230.4436 10132.6229.910510149.79231.004810160.91232.873410172.03231.7183
10178.35231.817610194.45232.725310228.23233.533310262.01235.688310337.03236.7053
#Mann= 3 , 0 , 0
9662.979  0.0749       09662.979  0.0749       010337.03  0.0749       0
#XS Ineff= 2 , 0
       0                               0
Bank Sta=9662.979,10337.03
Exp/Cntr=0.3,0.1

Type RM Length L Ch R = 1 ,4428.243,147.242900,147.242900,147.242900
XS GIS Cut Line= 6
816536.188736101788800.494613717816610.173619472788908.829596016
816718.865418319789082.450211513816735.764560253789110.150290849
 816789.53484636789203.457749089816884.046627817789377.326572246
#Sta/Elev= 30
9662.976268.68769714.063268.64949777.417267.98279872.231 264.3219878.642263.3074
9884.029262.20679895.827254.65789907.625241.79659916.333234.74419919.423231.4146
9931.221221.47529935.178 219.6379943.019217.70519954.024 217.55210049.94217.5813
10060.13219.123710069.97222.495510083.21 225.87110094.75231.3372 10106.3231.9378
10117.84229.954710152.28230.543710163.66 230.79510171.52231.542210175.04232.3009
10231.95233.770710243.33234.183110255.28235.102810277.48235.790710337.04236.3946
#Mann= 3 , 0 , 0
9662.976    0.12       09662.976    0.12       010337.04    0.12       0
#XS Ineff= 2 , 0
       0                               0
Bank Sta=9662.976,10337.04
Exp/Cntr=0.3,0.1

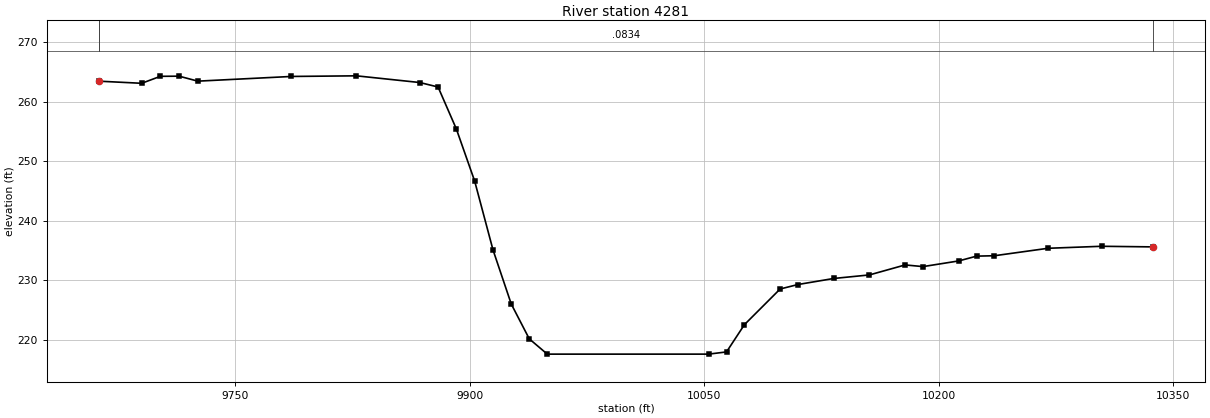
Type RM Length L Ch R = 1 ,    4281,0.000000,0.000000,0.000000
XS GIS Cut Line= 6
 816415.42784934788872.327632382816487.657785828788981.846786524
816556.779049917789095.520349605816592.447744129789157.826544908
816593.420524347789159.574028426816756.095530379789453.616328863
#Sta/Elev= 30
9662.974263.42599690.133263.07319702.112264.24459714.091264.2693 9726.07263.4329
9785.965 264.2239827.546264.32789868.079263.20239879.783262.44939891.487255.3899
 9903.19246.63849914.894235.10039926.597 225.977 9938.13 220.1199949.652 217.552
10052.91 217.55210064.34217.923910075.77222.498510098.63228.498310110.06229.2521
10132.91230.267310155.77230.864110178.63232.544210190.05232.262910212.91233.2164
10224.34234.022710235.77234.090110270.05235.342210304.34235.678410337.04235.5754
#Mann= 3 , 0 , 0
9662.974  0.0834       09662.974  0.0834       010337.04  0.0834       0
#XS Ineff= 2 , 0
       0                               0
Bank Sta=9662.974,10337.04
Exp/Cntr=0.3,0.1